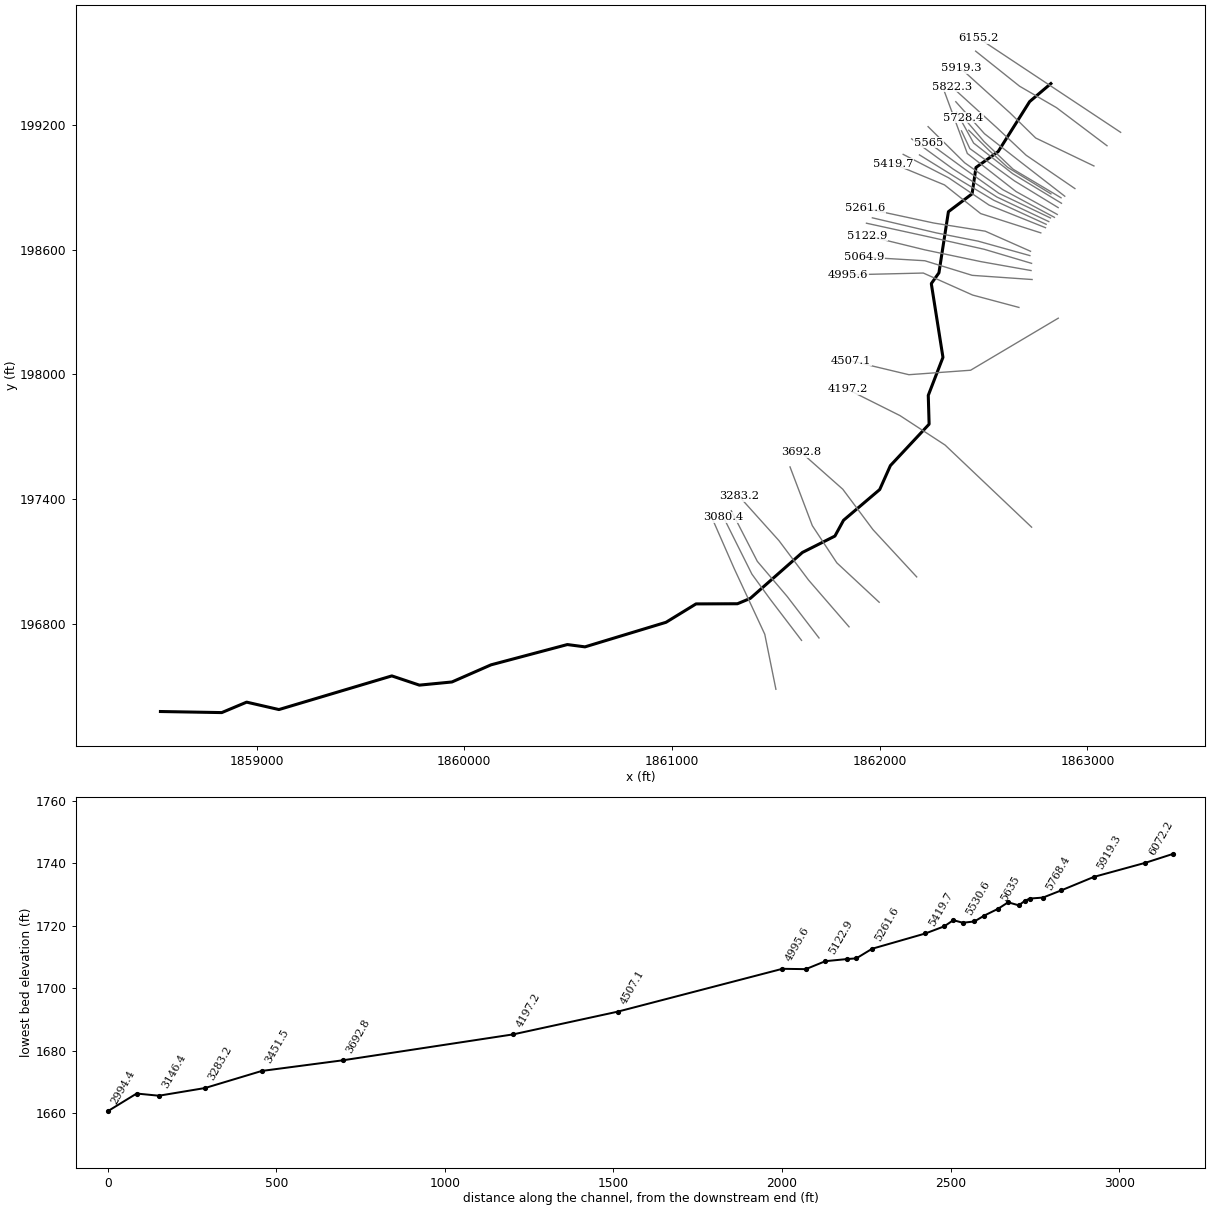
--- MillBr.prj (project) ---

Proj Title=MillBr
Current Plan=p01
Default Exp/Contr=0,0
English Units
Geom File=g01
Flow File=f01
Plan File=p01
BEGIN DESCRIPTION:
END DESCRIPTION:
DSS Export Rating Curves= 0
DSS Export Rating Curve Sorted= 0
DSS Export Volume Flow Curves= 0
DXF OffsetX= 0
DXF OffsetY= 0
DXF ScaleX= 0
DXF ScaleY= 0

--- MillBr.p01 (plan) ---

Plan Title=Floodplain
Program Version=4.00
Geom File=g01
Flow File=f01
K Sum by GR=0
Std Step Tol=0.01
Critical Tol=0.01
Num of Std Step Trials=20
Max Error Tol=0.3
Flow Tol Ratio=0.001
Split Flow NTrial=30
Split Flow Tol=0.02
Split Flow Ratio=0.02
Log Output Level=0
Friction Slope Method=1
Unsteady Friction Slope Method=2
Unsteady Bridges Friction Slope Method=1
Global Log Level=0
CheckData=False
Run HTab=0
Run UNet=0
Run PostProcess=0
UNET Theta=0
UNET Theta Warmup=0
UNET ZTol=0
UNET ZSATol=0
UNET MxIter=0
UNET MaxInSteps=0
UNET DtIC=0
UNET DtMin=0
UNET MaxCRTS=0
UNET WFStab=0
UNET SFStab=0
UNET WFX=0
UNET SFX=0
UNET DSS MLevel=0
UNET DZMax Abort=0
UNET Convert EG Bridges=0
UNET Use Existing IB Tables=0
UNET Froude Limit=0
UNET Froude Power=0
Write IC File=0
Echo Input=False
Echo Output=False
Write Detailed=0

--- MillBr.f01 (steady flow) ---

Flow Title=NFF Regression Equation
Program Version=4.00
Number of Profiles=1
Profile Names=P100yr
River Rch & RM=MillBr,Main      ,6155.2
498.8450
River Rch & RM=MillBr,Main      ,6072.2
603.2470
River Rch & RM=MillBr,Main      ,4507.1
657.0894
River Rch & RM=MillBr,Main      ,4197.2
814.4717
River Rch & RM=MillBr,Main      ,2994.4
859.5483
River Rch & RM=MillBr,Main      ,259.7
927.4986
Boundary for River Rch & Prof#=MillBr,Main      ,1
Up Type=0
Dn Type=3
Dn Slope=0.056952

--- MillBr.g01 (geometry) ---

Geom Title=USGS 10m DEM
Program Version=4.00

River Reach=MillBr          ,Main
Reach XY= 30
     1862824.286      199398.264     1862721.957      199311.531
     1862570.591      199071.334     1862463.642      198994.774
     1862444.941      198867.955     1862330.978      198782.045
     1862285.393       198488.08     1862248.575      198436.067
     1862304.679      198081.322     1862233.964      197898.398
     1862238.055       197759.89     1862051.624      197560.602
     1862000.195      197445.471     1861826.037      197297.612
     1861784.543      197221.637     1861627.918       197142.74
     1861377.099      196921.795     1861315.289       196896.04
     1861115.877      196895.304     1860971.561      196806.889
     1860581.218      196688.644     1860496.476      196699.748
     1860128.875      196602.149     1859940.691      196519.746
     1859784.066      196504.551     1859651.402      196548.967
     1859107.889      196387.082     1858952.433      196422.732
     1858832.626      196372.471     1858537.392      196377.664

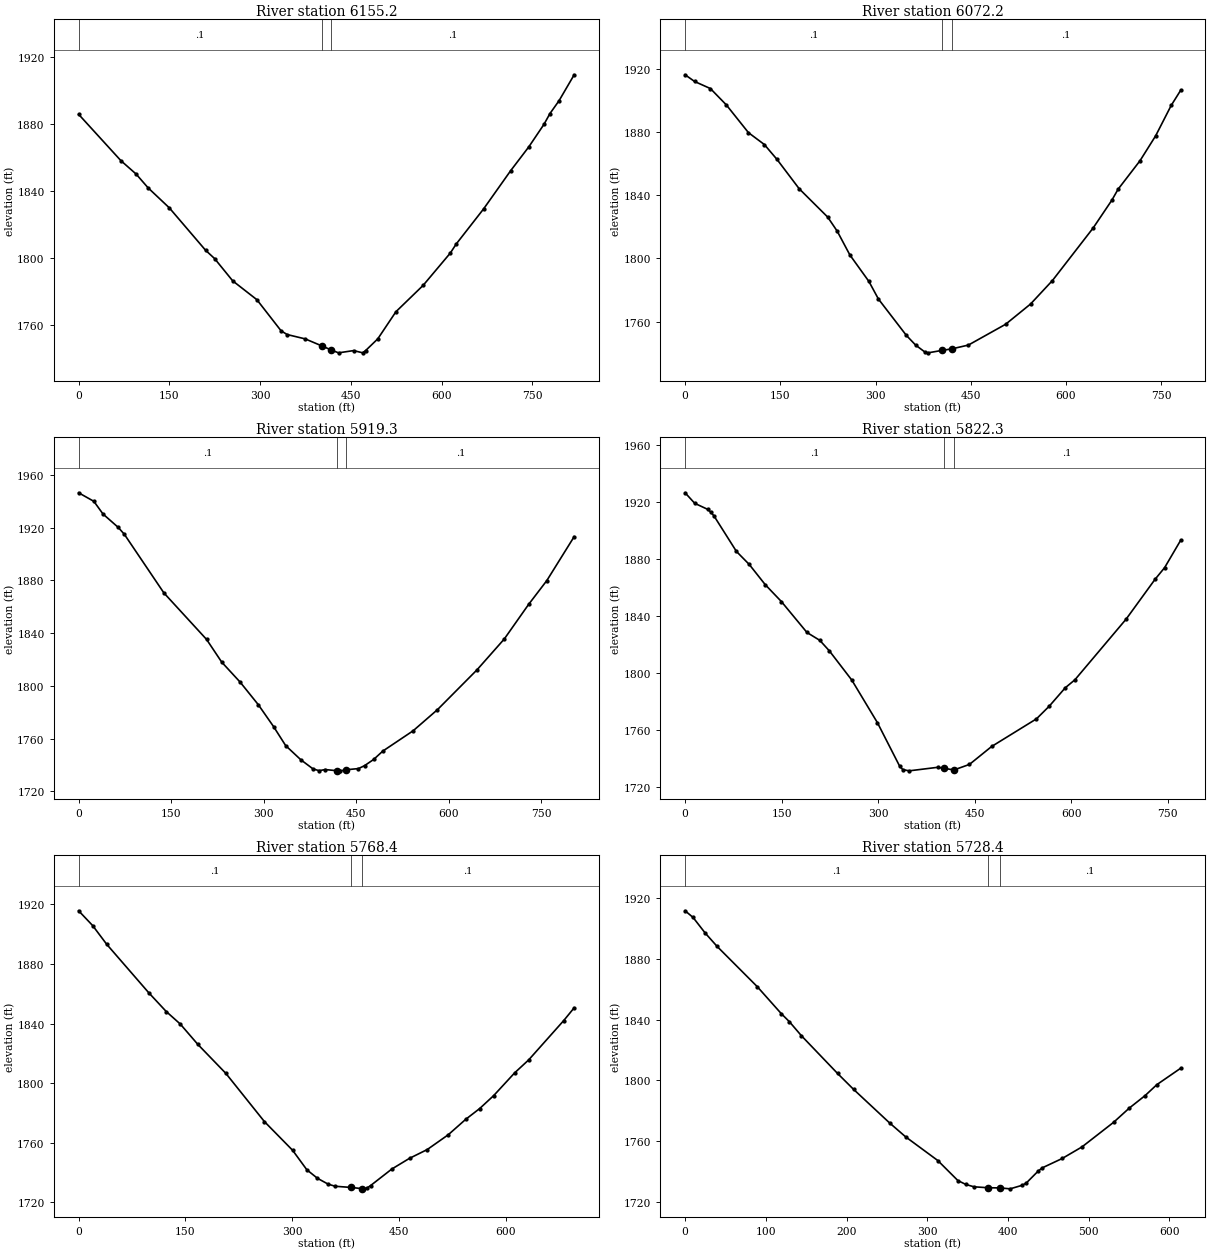
Type RM Length L Ch R = 1 ,6155.2  ,79.8,83,85
XS GIS Cut Line= 3
     1863160.137      199163.755     1862818.763      199389.927
     1862477.389        199616.1
#Sta/Elev= 30
       0 1885.91    69.9 1858.15    94.9 1850.18   114.9 1841.85   149.8 1829.93
   209.7 1804.54   224.7 1799.52   254.7 1786.15   294.6 1774.89   334.6 1756.25
   344.6 1754.02   374.5 1751.41     402  1747.2     417 1744.86   429.5 1743.06
   454.4  1744.4   469.4 1743.09   474.4 1744.45   494.4 1751.43   524.4 1767.68
   569.3 1783.44   614.2 1802.78   624.2 1808.32   669.2 1829.22   714.1 1852.19
   744.1 1866.47   769.1 1879.92     779 1886.39     794 1894.07     819  1909.6
#Mann= 3 , 0 , 0
       0      .1       0     402    .045       0     417      .1       0
Bank Sta=402,417
XS Rating Curve= 0 ,0
Exp/Cntr=0.3,0.1

Type RM Length L Ch R = 1 ,6072.2  ,160.8,152.9,146.1
XS GIS Cut Line= 4
     1863094.472      199099.282      1862851.22      199282.436
     1862673.789      199385.461     1862462.017      199554.306
#Sta/Elev= 30
       0 1916.51      15 1912.25    39.9 1907.76    64.9 1897.43    99.8  1879.8
   124.8 1872.29   144.8 1862.82   179.7 1844.23   224.6 1826.26   239.6 1817.32
   259.6  1802.2   289.5 1785.46   304.5 1774.29   348.5 1751.24   363.1 1745.08
   377.8 1740.65   382.7 1740.17   404.8 1741.73   419.8 1742.66   446.2  1745.1
   504.8 1758.28   544.1 1771.13   578.6 1786.03   642.6  1819.3   672.2    1837
     682 1843.94   716.5    1862   741.1 1877.77   765.7 1897.12   780.5 1906.63
#Mann= 3 , 0 , 0
       0      .1       0   404.8    .045       0   419.8      .1       0
Bank Sta=404.8,419.8
XS Rating Curve= 0 ,0
Exp/Cntr=0.3,0.1

Type RM Length L Ch R = 1 ,5919.3  ,96.1,97,97.9
XS GIS Cut Line= 4
     1863031.513      199001.981     1862751.057      199136.485
        1862628.       199256.68     1862390.472      199471.314
#Sta/Elev= 30
       0 1946.42    24.7 1939.93    39.5 1930.33    64.2 1920.17    74.1 1914.96
   138.2 1870.51   207.4 1835.25     232 1818.01   261.7 1802.95   291.3 1785.74
     316 1769.17   335.6 1754.76   360.2 1744.02   379.8 1737.16   389.7 1735.76
   399.5 1736.63   419.1 1735.72   424.1 1735.65   434.1  1736.5   453.6 1737.36
   463.4 1739.56   478.1 1744.25   492.9 1750.57   542.2 1766.02   581.6 1782.01
   645.6 1812.15   689.9 1835.58   729.3 1861.77   758.9  1879.9   803.2 1913.17
#Mann= 3 , 0 , 0
       0      .1       0   419.1    .045       0   434.1      .1       0
Bank Sta=419.1,434.1
XS Rating Curve= 0 ,0
Exp/Cntr=0.3,0.1

Type RM Length L Ch R = 1 ,5822.3  ,51.9,53.9,55.9
XS GIS Cut Line= 4
     1862939.935      198893.233     1862705.269      199053.493
     1862565.041      199185.135     1862347.545      199382.599
#Sta/Elev= 30
       0 1926.41      15 1919.01    34.9 1914.83    39.9 1912.83    44.9 1910.18
    79.8 1885.26    99.7 1876.13   124.6 1861.93   149.6 1850.13   189.4 1828.41
   209.4 1822.87   224.3 1815.47   259.2 1794.95     299 1765.08   333.5 1734.61
   338.4  1732.2   348.3 1731.32   392.7  1733.8   402.9 1733.06   417.9 1731.95
     442 1735.82   476.5  1748.4   546.2  1767.8   566.1 1776.71     591 1789.61
     606 1795.22   685.6 1837.79   730.4 1865.63   745.4 1873.88   770.3 1893.04
#Mann= 3 , 0 , 0
       0      .1       0   402.9    .045       0   417.9      .1       0
Bank Sta=402.9,417.9
XS Rating Curve= 0 ,0
Exp/Cntr=0.3,0.1

Type RM Length L Ch R = 1 ,5768.4  ,42.3,40,37.7
XS GIS Cut Line= 4
     1862891.085      198856.493     1862680.785      199019.306
     1862504.404      199157.245     1862366.465      199311.013
#Sta/Elev= 30
       0 1915.77    19.7 1905.84    39.4  1893.3    98.5 1860.74   123.1 1848.12
   142.8 1839.72   167.5 1826.05   206.9 1806.57     261 1774.24   300.8 1754.87
   320.7 1741.84   335.6 1736.12   350.6 1732.19   360.5 1730.76   382.9 1729.97
   397.9 1729.19   400.3 1729.03   405.3 1729.59   410.3 1731.22   440.1 1742.32
     465 1749.52   489.9 1755.41   519.4 1765.33     544 1775.72   563.6 1782.95
   583.3 1791.65   612.8 1806.94   632.5 1815.64   681.7 1842.03   696.4 1850.61
#Mann= 3 , 0 , 0
       0      .1       0   382.9    .045       0   397.9      .1       0
Bank Sta=382.9,397.9
XS Rating Curve= 0 ,0
Exp/Cntr=0.3,0.1

Type RM Length L Ch R = 1 ,5728.4  ,13.5,14.2,14.8
XS GIS Cut Line= 4
     1862873.153       198848.94     1862642.673      198986.169
     1862502.075      199119.866     1862403.527      199234.945
#Sta/Elev= 30
       0 1911.56     9.9 1907.16    24.8 1896.98    39.7  1888.1    89.4 1861.65
   119.2 1843.88   129.2 1838.61     144 1829.43   188.8 1804.61   208.6 1794.16
   253.3 1772.04   273.2 1762.88     313 1747.32   337.9 1734.14   347.8 1731.58
   357.8 1730.04     375 1729.43     390 1729.31   402.6  1728.7   417.5 1731.03
   422.5 1732.47   437.4 1740.41   442.4  1742.5   467.1 1748.66   491.6 1756.27
   530.7 1772.42   550.2 1781.81   569.8 1790.03   584.4 1797.24   613.8    1808
#Mann= 3 , 0 , 0
       0      .1       0     375    .045       0     390      .1       0
Bank Sta=375,390
XS Rating Curve= 0 ,0
Exp/Cntr=0.3,0.1

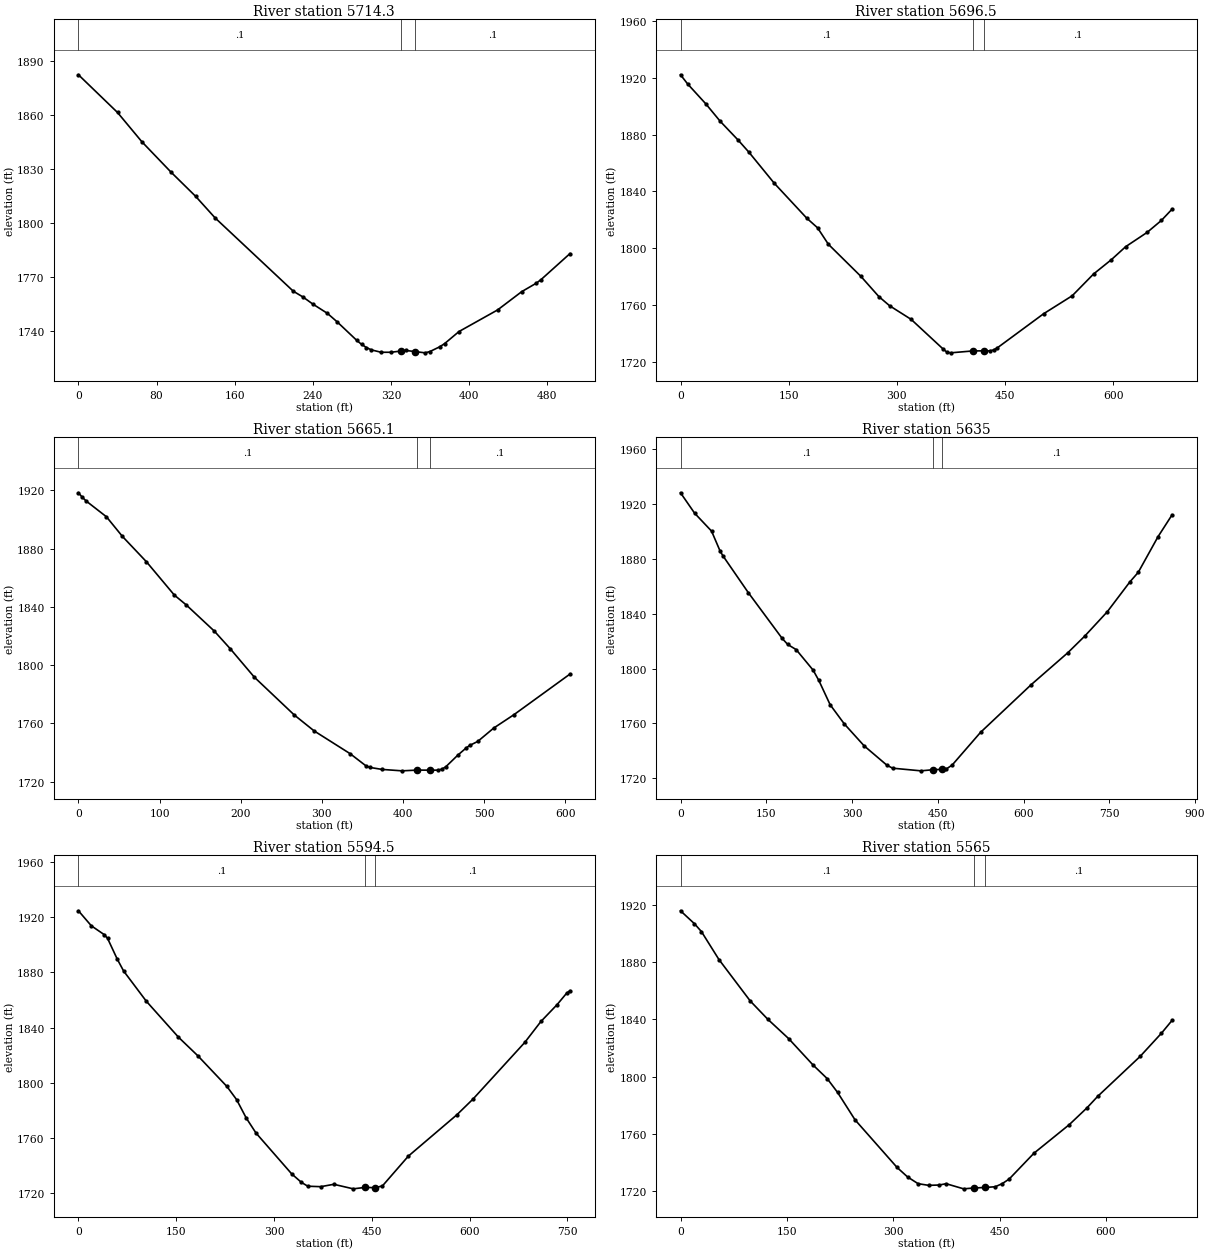
Type RM Length L Ch R = 1 ,5714.3  ,15.7,17.8,19.8
XS GIS Cut Line= 4
     1862824.578      198867.728     1862615.789      198995.625
     1862527.246      199076.517     1862428.863      199173.806
#Sta/Elev= 30
       0 1882.42      40 1861.48      65 1845.17    94.9 1828.26   119.9 1814.93
   139.9  1802.9   219.9 1762.19   229.9 1758.94   239.8 1755.08   254.8 1749.89
   264.8 1745.17   284.8  1734.9   289.8 1732.64   294.8  1730.9   299.8 1729.59
   309.8 1728.27   319.8 1728.27   329.8 1728.92   334.8 1729.29   344.8 1728.64
   354.8 1727.95   359.8 1728.68   369.7 1731.29   374.7 1733.04   389.5 1739.78
     429 1751.78   453.7 1761.94   468.6 1766.64   473.5 1768.64   503.1 1783.09
#Mann= 3 , 0 , 0
       0      .1       0   329.8    .045       0   344.8      .1       0
Bank Sta=329.8,344.8
XS Rating Curve= 0 ,0
Exp/Cntr=0.3,0.1

Type RM Length L Ch R = 1 ,5696.5  ,30.5,31.4,32.3
XS GIS Cut Line= 4
     1862875.256      198822.574     1862640.081      198965.035
     1862452.394      199112.019     1862370.988      199259.003
#Sta/Elev= 30
       0 1922.02      10  1915.5      35 1901.63      55 1889.34      80 1876.04
      95 1867.49     130 1845.75     175 1821.22     190 1814.43     205 1802.85
     250 1780.34     275 1766.07   289.9 1759.63   319.7 1750.07   364.4 1729.05
   369.3 1727.01   374.3 1726.54   405.1 1727.87   420.1 1727.95   428.9  1727.9
   433.9 1728.57   438.8  1729.9   503.4 1754.04     543 1766.67   572.6 1781.97
   597.4 1792.09   617.1 1801.18   646.8  1811.2   666.6 1819.62   681.4 1827.54
#Mann= 3 , 0 , 0
       0      .1       0   405.1    .045       0   420.1      .1       0
Bank Sta=405.1,420.1
XS Rating Curve= 0 ,0
Exp/Cntr=0.3,0.1

Type RM Length L Ch R = 1 ,5665.1  ,31.5,30.1,28.6
XS GIS Cut Line= 4
     1862859.349      198801.593     1862649.093      198929.993
     1862434.022      199085.679     1862393.897      199170.744
#Sta/Elev= 30
       0 1918.33     4.9 1915.15     9.8 1912.56    34.5 1901.87    54.2  1888.4
    83.8    1871   118.2 1848.14     133 1841.32   167.5  1823.4   187.2 1811.26
   216.8  1791.8     266 1765.87   290.6 1754.88   334.9 1739.28   354.5  1730.9
   359.4 1729.84   374.2 1728.49   398.8 1727.51   417.9 1728.02   432.9 1727.97
     443 1727.98     448 1728.65   452.9 1730.33   467.6 1738.26   477.4 1742.96
   482.4 1744.98   492.2 1747.69   511.9 1756.87   536.6 1765.96   605.9 1793.92
#Mann= 3 , 0 , 0
       0      .1       0   417.9    .045       0   432.9      .1       0
Bank Sta=417.9,432.9
XS Rating Curve= 0 ,0
Exp/Cntr=0.3,0.1

Type RM Length L Ch R = 1 ,5635    ,39.8,40.5,41.6
XS GIS Cut Line= 4
     1862855.073      198768.764     1862656.618      198878.924
     1862421.951      199062.078     1862305.655      199376.285
#Sta/Elev= 30
       0 1928.16    24.7 1913.26    54.3 1900.21    69.1 1885.81      74 1882.32
   118.4 1855.45   177.6 1822.08   187.5 1817.56   202.3  1813.8   231.9 1798.86
   241.9 1791.35   261.7 1773.63   286.5 1759.62   321.2 1743.63   360.9 1729.56
   370.9 1727.36   420.5 1725.42     442 1726.24     457 1726.49   465.1 1726.88
     475 1729.59   524.7 1753.46   613.4 1788.28   677.4 1811.54     707 1823.66
   746.4 1841.41   785.8 1863.12   800.6 1870.17   835.1 1896.11   859.7 1912.05
#Mann= 3 , 0 , 0
       0      .1       0     442    .045       0     457      .1       0
Bank Sta=442,457
XS Rating Curve= 0 ,0
Exp/Cntr=0.3,0.1

Type RM Length L Ch R = 1 ,5594.5  ,32.1,29.5,27.1
XS GIS Cut Line= 4
     1862841.336      198754.735     1862592.594      198888.151
      1862409.43      199017.045     1862233.049      199191.164
#Sta/Elev= 30
       0 1924.54    19.8 1913.66    39.6 1907.26    44.6 1904.67    59.4 1889.69
    69.3 1880.96     104 1859.16   153.5 1833.02   183.2 1819.58   227.8 1797.36
   242.6 1787.89   257.5 1774.48   272.4 1763.68   327.1 1734.13     342 1727.97
   351.9 1725.16   371.8 1724.84   391.8 1726.55   421.6 1723.27   440.3 1724.34
   455.3 1724.07   466.4  1725.4   506.2 1746.98   580.6 1776.88   605.4 1788.28
   684.7 1829.22   709.5  1844.4   734.2 1856.53   749.1 1864.96   754.1 1866.68
#Mann= 3 , 0 , 0
       0      .1       0   440.3    .045       0   455.3      .1       0
Bank Sta=440.3,455.3
XS Rating Curve= 0 ,0
Exp/Cntr=0.3,0.1

Type RM Length L Ch R = 1 ,5565    ,32.8,34.4,35.5
XS GIS Cut Line= 4
     1862822.434      198751.837     1862573.658      198870.608
     1862408.342      198987.774     1862235.001      199114.569
#Sta/Elev= 30
       0 1916.01    19.7 1906.93    29.5 1901.45    54.2 1881.88    98.4 1852.83
   123.1 1840.07   152.6 1826.48   187.1 1807.94   206.8 1798.56   221.5 1788.86
   246.1 1769.67   305.3 1736.39   320.2 1729.69     335 1724.99   349.8 1723.83
   364.6 1724.04   374.5 1724.97   399.2 1721.38   413.9 1721.98   428.9 1722.32
   443.7 1722.84   453.6 1725.01   463.5 1728.26   498.3 1746.29   548.2 1766.33
   573.2  1778.1   588.2 1786.09   648.1 1814.08   678.1 1830.28   693.1 1839.28
#Mann= 3 , 0 , 0
       0      .1       0   413.9    .045       0   428.9      .1       0
Bank Sta=413.9,428.9
XS Rating Curve= 0 ,0
Exp/Cntr=0.3,0.1

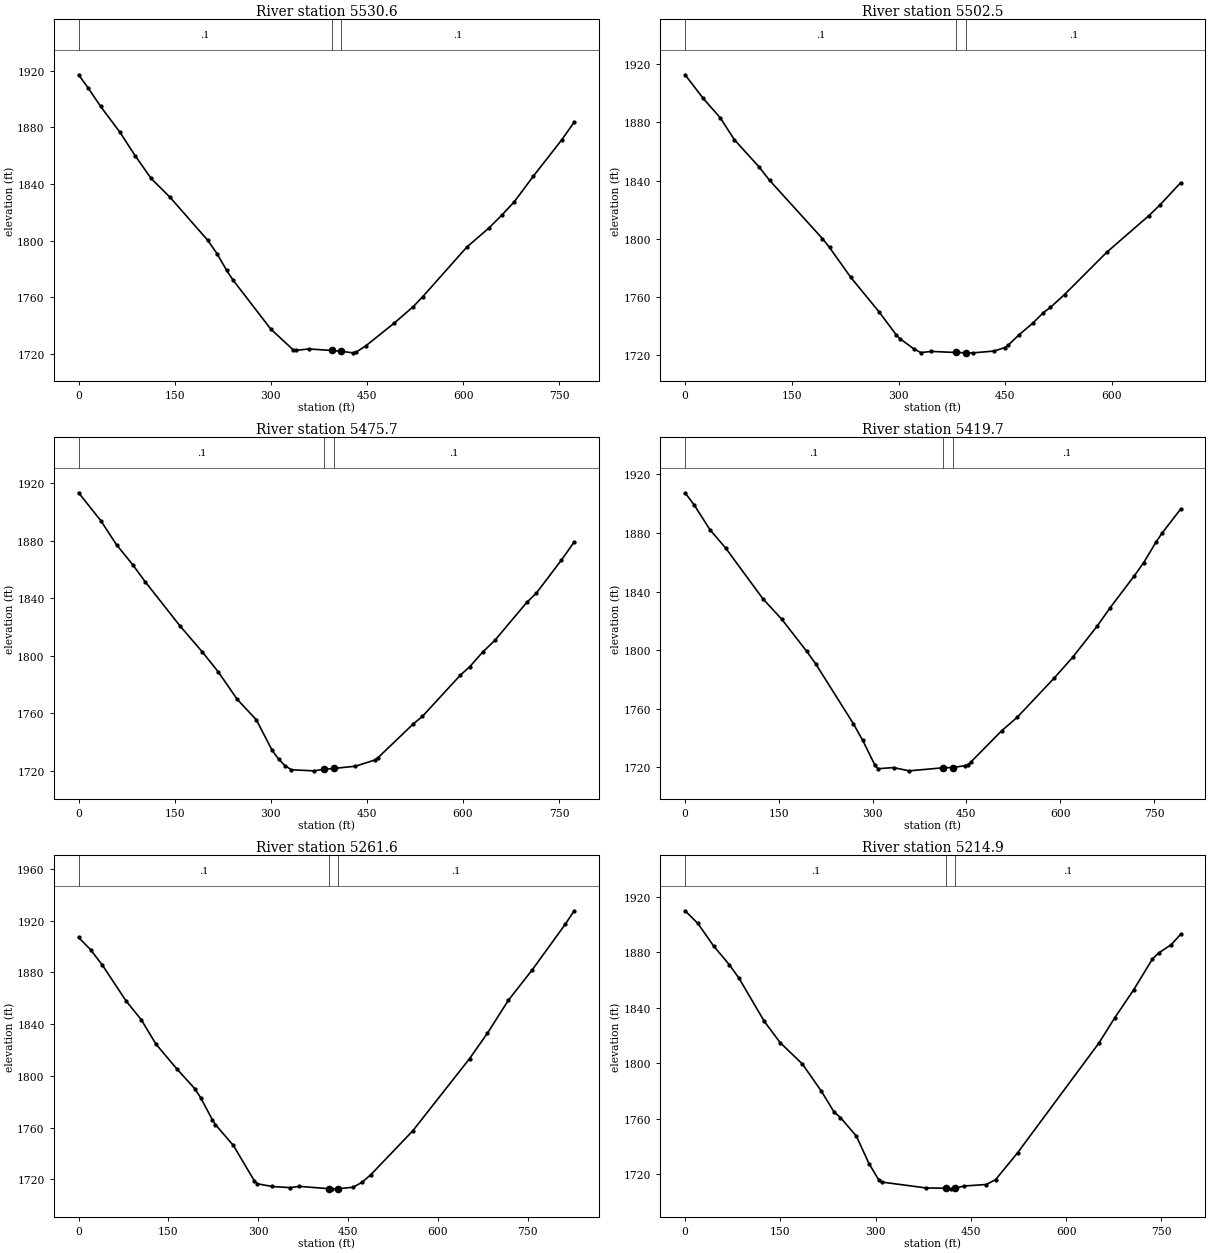
Type RM Length L Ch R = 1 ,5530.6  ,25.1,28.1,31.1
XS GIS Cut Line= 4
     1862814.201      198734.383     1862565.459      198851.971
     1862352.897      198987.648     1862153.904      199132.371
#Sta/Elev= 30
       0 1917.09    14.7 1907.91    34.4 1894.72    63.9 1876.91    88.4 1859.91
     113 1844.04   142.5 1830.76   201.4 1800.41   216.2 1790.78   230.9  1779.2
   240.7 1772.46   299.9 1737.72   334.5 1723.23   339.4 1722.72   359.2  1723.7
   395.2 1722.62   410.2    1722   428.4 1720.96   433.4 1721.55   448.2 1725.88
   492.7 1741.99   522.4 1753.62   537.2 1760.65     606 1795.63   640.5 1809.06
   660.2 1817.98   679.9 1827.48   709.4 1845.41   753.7 1871.04   773.4 1883.65
#Mann= 3 , 0 , 0
       0      .1       0   395.2    .045       0   410.2      .1       0
Bank Sta=395.2,410.2
XS Rating Curve= 0 ,0
Exp/Cntr=0.3,0.1

Type RM Length L Ch R = 1 ,5502.5  ,28.2,26.8,26.1
XS GIS Cut Line= 4
     1862801.569      198721.342     1862549.583      198836.903
     1862401.922      198925.178     1862191.666      199055.184
#Sta/Elev= 30
       0 1912.73    24.8 1896.91    49.5 1883.13    69.3 1868.13     104 1849.43
   118.8  1840.2   193.1 1800.21     203 1794.13   232.7 1773.72   272.3 1750.13
   296.9 1734.06   301.8 1731.57   321.5 1724.52   331.3 1721.95     346 1722.76
   380.4 1722.03   395.4 1721.84     405 1721.79   434.5 1723.02   449.3 1725.42
   454.2 1727.08     469 1734.02   488.8 1742.22   503.6 1749.41   513.5    1753
   533.3 1761.83   592.6 1790.84     652 1816.04   666.8 1823.02   696.5 1838.61
#Mann= 3 , 0 , 0
       0      .1       0   380.4    .045       0   395.4      .1       0
Bank Sta=380.4,395.4
XS Rating Curve= 0 ,0
Exp/Cntr=0.3,0.1

Type RM Length L Ch R = 1 ,5475.7  ,58.2,56,52.9
XS GIS Cut Line= 4
     1862798.372      198704.987     1862527.017      198813.529
     1862332.546      198944.684       1862113.2      199057.748
#Sta/Elev= 30
       0 1913.45    34.7 1893.97    59.4 1877.09    84.2  1863.5     104 1851.46
   158.5 1820.59   193.2 1802.57     218 1788.72   247.7 1769.55   277.4 1755.38
   302.2 1734.01   312.2 1727.97   322.2 1723.39   332.2 1720.55   367.1 1719.82
   383.5 1720.91   398.5 1721.48     432 1723.04   461.9 1727.26   466.9 1728.78
   521.8 1752.23   536.7 1757.74   595.9 1786.46   610.7 1792.38   630.5 1802.39
   650.2 1810.89   699.6 1837.12   714.4 1843.51   753.8 1866.66   773.6 1879.19
#Mann= 3 , 0 , 0
       0      .1       0   383.5    .045       0   398.5      .1       0
Bank Sta=383.5,398.5
XS Rating Curve= 0 ,0
Exp/Cntr=0.3,0.1

Type RM Length L Ch R = 1 ,5419.7  ,146.9,158.1,169.3
XS GIS Cut Line= 4
     1862775.759      198680.112     1862486.314      198772.826
     1862312.194      198910.764     1862065.713      199012.522
#Sta/Elev= 30
       0 1907.42      15 1898.82    39.9 1882.12    64.8 1869.72   124.6 1834.96
   154.5 1821.11   194.3 1799.29   209.3 1790.35     269 1749.84     284 1738.43
   303.9  1721.2   308.9 1718.99   333.6 1719.76   358.2 1717.53   413.2 1719.62
   428.2 1719.78   447.1 1721.02     452 1721.67     457 1723.48   506.3 1744.85
     531 1753.98   590.3 1780.83   619.9 1795.05   659.4 1816.48   679.2 1828.49
   718.7 1850.76   733.5 1859.64   753.2 1873.68   763.1 1879.93   792.7 1896.28
#Mann= 3 , 0 , 0
       0      .1       0   413.2    .045       0   428.2      .1       0
Bank Sta=413.2,428.2
XS Rating Curve= 0 ,0
Exp/Cntr=0.3,0.1

Type RM Length L Ch R = 1 ,5261.6  ,47.6,46.7,45.8
XS GIS Cut Line= 4
     1862726.325      198591.582     1862508.257      198688.203
     1862261.691      198727.249     1861929.574      198798.386
#Sta/Elev= 30
       0 1907.06    19.9 1897.65    39.8 1885.61    79.5 1857.81   104.4 1843.62
   129.2 1824.56     164 1805.44   193.8 1790.24   203.7 1783.26   223.6 1765.89
   228.6 1762.26   258.5  1746.2   293.4 1718.93   298.4 1716.54   323.4 1714.45
   353.4 1713.56   368.3 1714.54   417.8 1712.76   423.2 1712.63   432.8 1712.68
   458.2 1713.86   473.2 1717.59   488.2 1723.61   558.1 1757.47     653 1813.34
     683  1833.1   717.9 1858.51   757.9 1882.12   812.8 1917.23   827.8 1927.72
#Mann= 3 , 0 , 0
       0      .1       0   417.8    .045       0   432.8      .1       0
Bank Sta=417.8,432.8
XS Rating Curve= 0 ,0
Exp/Cntr=0.3,0.1

Type RM Length L Ch R = 1 ,5214.9  ,28.5,27.9,27.3
XS GIS Cut Line= 4
      1862723.19      198570.805     1862473.135      198640.492
     1862272.272      198680.118     1861964.827      198752.539
#Sta/Elev= 30
       0 1909.79      20 1900.73    44.9 1884.43    69.9 1870.82    84.9 1861.19
   124.8 1830.08   149.8 1814.79   184.7 1799.44   214.7 1779.78   234.6 1764.84
   244.6 1760.88   269.6 1747.56   289.5  1727.8   304.5 1716.24   309.5 1714.45
   379.4  1710.2   410.1 1710.01   419.4 1709.56   425.1 1710.11   439.4  1711.6
   474.2 1712.68     489 1716.26   523.5 1735.53   651.9  1814.8   676.5 1832.76
   706.2 1852.85   735.8 1875.08   745.6 1879.37   765.4 1885.42   780.2 1892.85
#Mann= 3 , 0 , 0
       0      .1       0   410.1    .045       0   425.1      .1       0
Bank Sta=410.1,425.1
XS Rating Curve= 0 ,0
Exp/Cntr=0.3,0.1

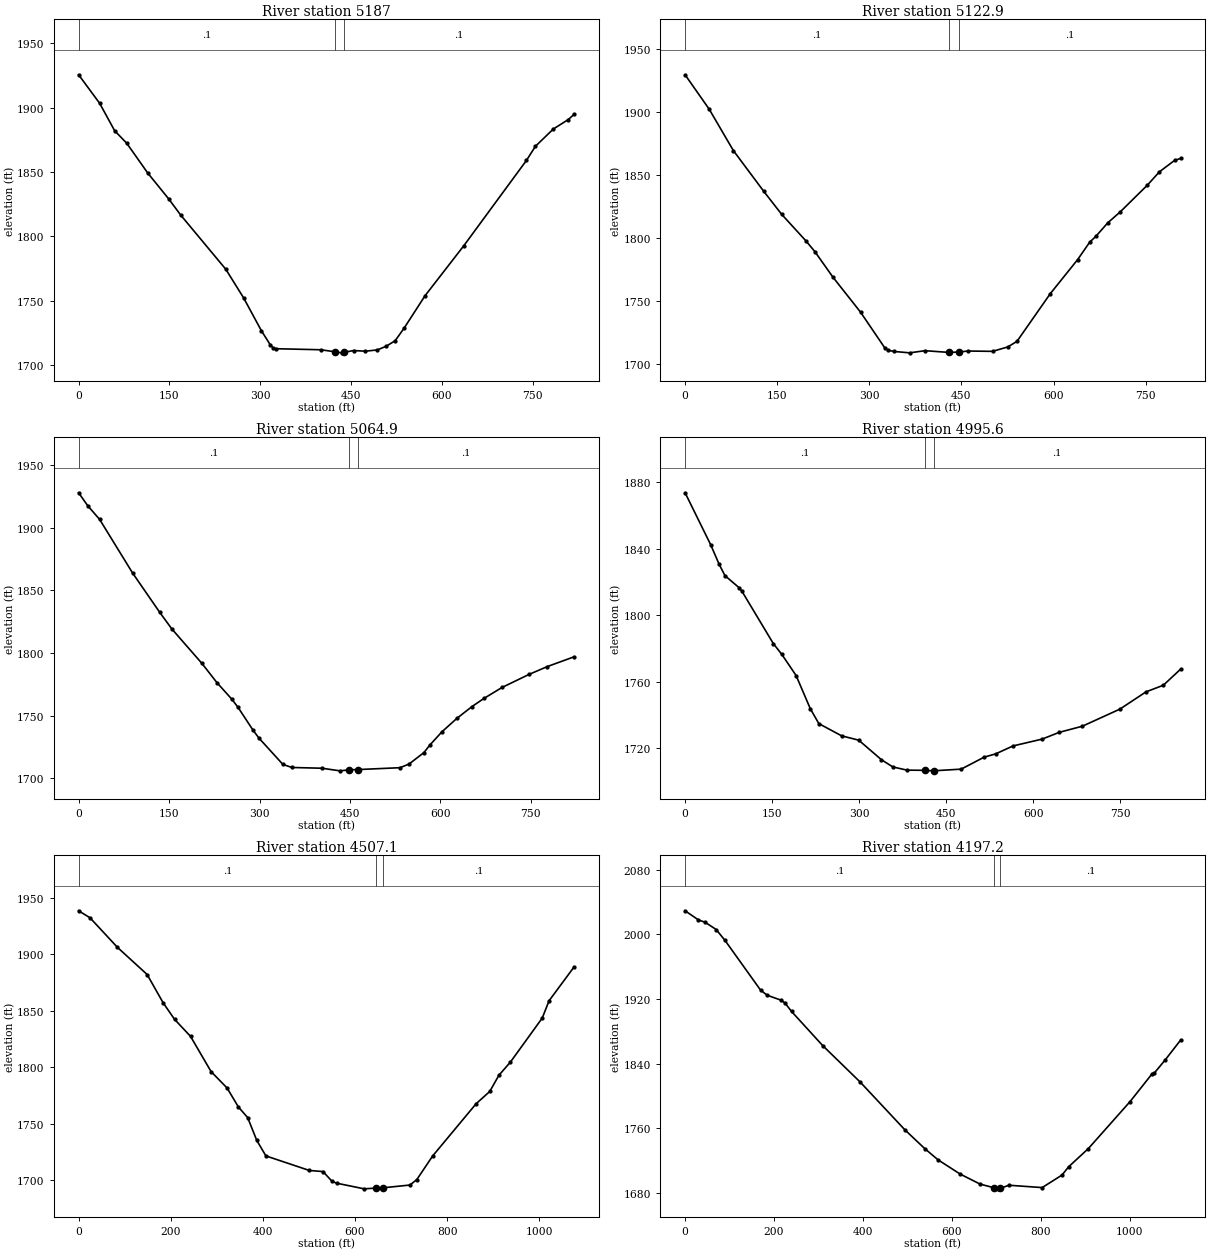
Type RM Length L Ch R = 1 ,5187    ,63.8,64.1,64.4
XS GIS Cut Line= 4
      1862731.35      198533.506     1862503.138      198601.217
     1862234.801      198661.405     1861936.369      198726.609
#Sta/Elev= 30
       0 1925.45    34.7 1903.29    59.5 1881.96    79.4 1872.29   114.1 1849.12
   148.8 1828.96   168.6  1816.4     243 1774.34   272.4 1752.13   301.9  1726.5
   316.6 1715.53   321.5 1713.12   326.4 1712.53   400.1 1711.72   423.1 1710.17
   434.5 1709.33   438.1 1709.69   454.1 1711.11   473.8  1710.6   493.4 1711.61
   508.1 1714.48   522.9 1718.78   537.7 1728.59   572.2 1753.73   636.2 1792.58
   739.7  1858.9   754.5 1869.87     784 1883.27   808.7 1890.62   818.5 1894.74
#Mann= 3 , 0 , 0
       0      .1       0   423.1    .045       0   438.1      .1       0
Bank Sta=423.1,438.1
XS Rating Curve= 0 ,0
Exp/Cntr=0.3,0.1

Type RM Length L Ch R = 1 ,5122.9  ,60.1,58,55.9
XS GIS Cut Line= 4
     1862728.765       198498.92     1862486.807      198541.885
     1862217.713      198598.417     1861939.574      198666.256
#Sta/Elev= 30
       0 1929.75    39.3 1902.34    78.6 1869.49   127.8 1837.26   157.3 1818.76
   196.6 1797.77   211.3 1789.17   240.8  1768.8   285.7 1741.01   325.7 1712.23
   330.7  1710.7   340.7 1709.73   365.7 1708.65   390.7 1710.36   430.3 1708.97
   445.3 1709.28   460.7 1710.09   500.7 1709.83   525.6 1713.36   540.5  1717.8
   594.8 1755.76   639.2 1782.74   658.9 1796.65   668.8  1801.2   688.5 1812.12
   708.3 1820.58   752.7 1841.93   772.4 1852.57   797.1 1861.66     807 1863.27
#Mann= 3 , 0 , 0
       0      .1       0   430.3    .045       0   445.3      .1       0
Bank Sta=430.3,445.3
XS Rating Curve= 0 ,0
Exp/Cntr=0.3,0.1

Type RM Length L Ch R = 1 ,5064.9  ,71.9,69.3,67.5
XS GIS Cut Line= 4
     1862733.858      198455.763     1862445.458      198475.826
     1862217.246      198546.045      1861923.83        198563.6
#Sta/Elev= 30
       0 1927.75      15 1917.49    34.9 1906.46    89.7 1863.63   134.6 1832.37
   154.5 1819.25   204.4 1791.78   229.3 1776.45   254.2 1763.12   264.2 1756.81
   289.1 1738.61     299 1732.22   338.8 1711.19   353.8 1708.78   403.5 1708.18
   433.4  1706.1     449  1706.9     464 1707.13   532.8  1708.6   547.8 1711.46
   572.7 1720.68   582.7 1726.79   602.6 1737.27   627.5 1748.01   652.4 1757.36
   672.4 1763.88   702.2 1772.58   747.1 1782.99     777 1789.17   821.8 1797.03
#Mann= 3 , 0 , 0
       0      .1       0     449    .045       0     464      .1       0
Bank Sta=449,464
XS Rating Curve= 0 ,0
Exp/Cntr=0.3,0.1

Type RM Length L Ch R = 1 ,4995.6  ,466.7,488.6,499.9
XS GIS Cut Line= 4
     1862670.418      198321.501     1862447.708      198380.972
     1862210.179      198486.859     1861846.732      198478.273
#Sta/Elev= 30
       0 1873.68    44.1 1842.38    58.8 1830.52    68.7 1823.78    93.2 1816.47
    98.1 1814.29     152 1782.89   166.8 1776.29   191.3 1763.63   215.8 1743.64
   230.5 1734.66   269.8 1727.29   299.2 1724.69   338.5 1712.88   358.1 1708.55
   382.6 1706.63   413.5 1706.52   426.8 1706.21   428.5 1706.24   475.8 1707.23
   515.5 1714.46   535.4 1716.44   565.3 1721.22   615.1  1725.3     645  1729.4
   684.8  1733.1   749.5  1743.4   794.4 1753.78   824.2 1757.75   854.1 1767.46
#Mann= 3 , 0 , 0
       0      .1       0   413.5    .045       0   428.5      .1       0
Bank Sta=413.5,428.5
XS Rating Curve= 0 ,0
Exp/Cntr=0.3,0.1

Type RM Length L Ch R = 1 ,4507.1  ,324.2,309.8,295.4
XS GIS Cut Line= 4
     1862859.805       198269.72     1862437.691      198019.314
     1862140.781       197997.85     1861861.507      198064.445
#Sta/Elev= 30
       0 1938.68    24.8 1932.43    84.3 1906.27   148.7 1882.25   183.4 1857.22
   208.2 1842.58   242.9 1827.47   287.5 1796.28   322.2 1781.77     347 1764.84
   366.9 1755.57   386.7 1735.34   406.5 1721.63   500.7 1708.76   530.5 1707.76
   550.3 1699.02   560.3 1697.46   619.8 1692.48   645.6 1693.16   660.6  1693.4
     719 1695.84   733.9  1700.6   768.6 1721.67   862.7  1767.8   892.4 1778.71
   912.2 1793.03     937 1804.59  1006.3  1843.7  1021.1    1859  1075.6 1889.07
#Mann= 3 , 0 , 0
       0      .1       0   645.6    .045       0   660.6      .1       0
Bank Sta=645.6,660.6
XS Rating Curve= 0 ,0
Exp/Cntr=0.3,0.1

Type RM Length L Ch R = 1 ,4197.2  ,512.6,504.4,496.1
XS GIS Cut Line= 4
     1862731.452      197264.405     1862314.863      197659.493
     1862097.854      197801.102     1861845.901      197927.071
#Sta/Elev= 30
       0 2029.12      30 2017.82    44.9 2014.95    69.9 2005.96    89.9 1992.39
   169.8    1931   184.7 1924.66   214.7 1918.79   224.7 1915.12   239.6 1904.56
   309.5 1862.43   394.4 1817.04   494.3 1758.33   539.2 1734.98   569.2 1721.06
     619 1703.45   663.8 1691.06   694.3 1686.67   703.7 1685.21   709.3 1685.81
   728.6 1689.66   803.4 1686.76   848.1 1702.27   862.9 1712.43   907.4 1735.03
  1001.3 1793.17  1050.7 1827.42  1055.7 1828.36  1080.4 1844.76    1115 1869.23
#Mann= 3 , 0 , 0
       0      .1       0   694.3    .045       0   709.3      .1       0
Bank Sta=694.3,709.3
XS Rating Curve= 0 ,0
Exp/Cntr=0.3,0.1

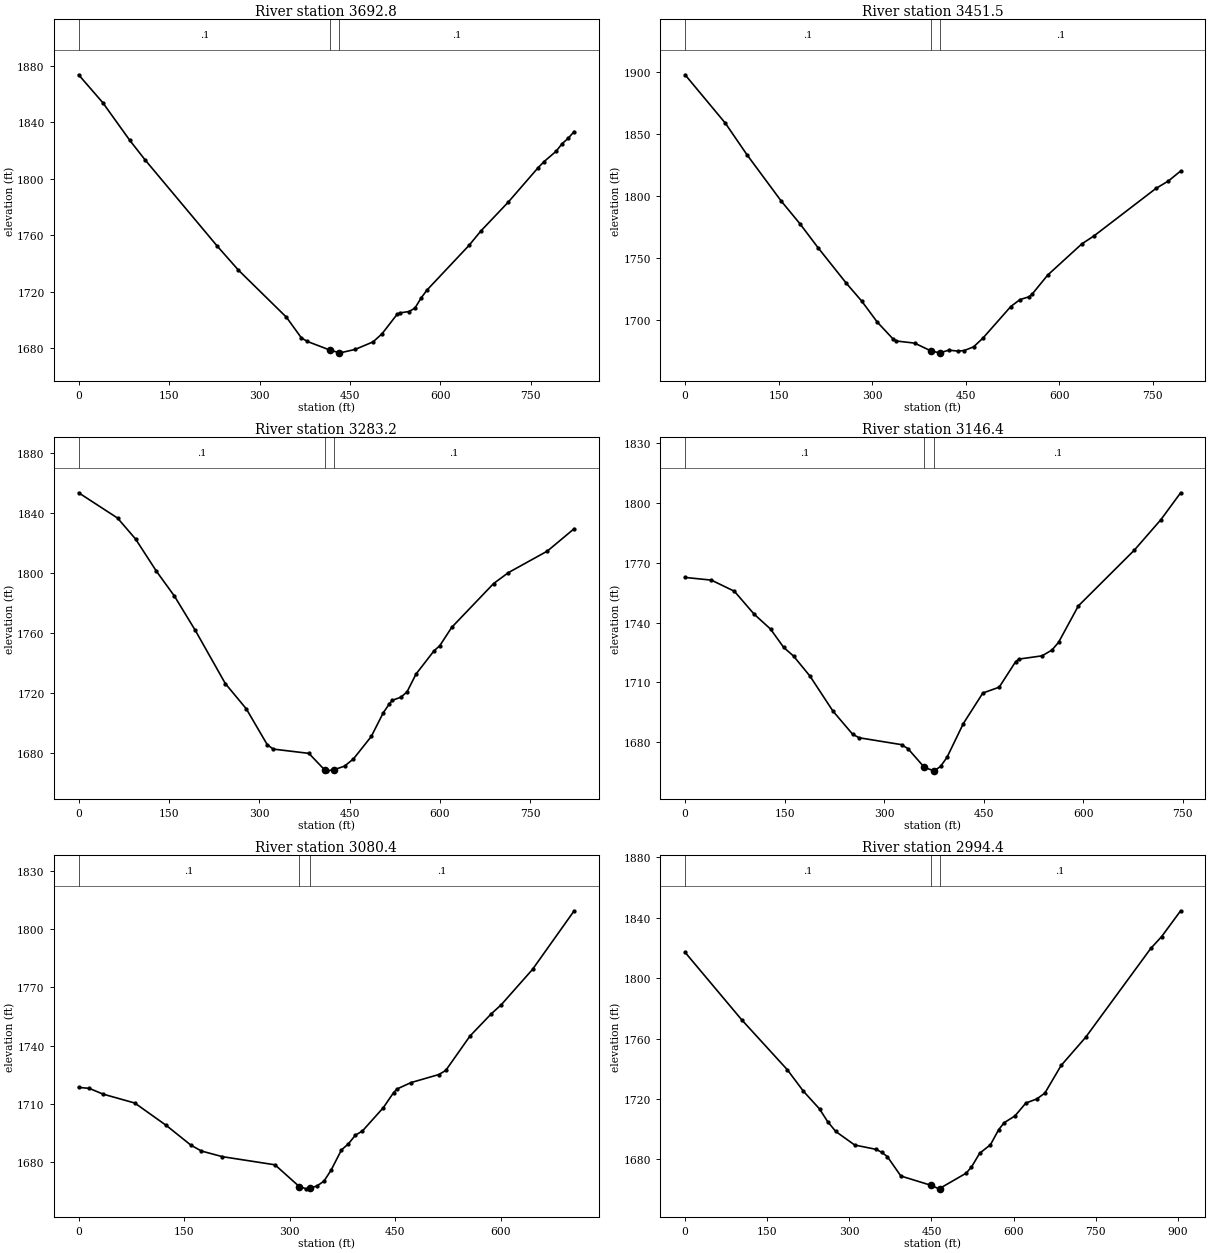
Type RM Length L Ch R = 1 ,3692.8  ,242.5,241.4,240.2
XS GIS Cut Line= 4
     1862178.274      197025.143     1861967.731      197252.542
     1861822.406      197446.956     1861620.917       197625.24
#Sta/Elev= 30
       0 1873.78      40 1854.06      85 1827.27     110 1813.63   229.9 1752.45
   264.9 1735.51   344.6 1702.12   369.3 1687.54   379.2    1685   417.3 1678.77
   432.3    1677   433.7 1676.92   458.5 1679.34   488.2 1684.67   503.1  1690.4
   527.9 1704.09   532.8 1705.18   547.7 1706.18   557.6 1708.53   567.6 1715.55
   577.5 1721.32   647.3 1752.97   667.2 1763.29   712.1 1783.48   761.9 1807.99
   771.8 1812.32   791.8 1819.64   801.7 1824.98   811.7 1828.79   821.7 1833.61
#Mann= 3 , 0 , 0
       0      .1       0   417.3    .045       0   432.3      .1       0
Bank Sta=417.3,432.3
XS Rating Curve= 0 ,0
Exp/Cntr=0.3,0.1

Type RM Length L Ch R = 1 ,3451.5  ,166.9,168.3,169.7
XS GIS Cut Line= 4
     1861997.691      196903.215     1861793.789      197092.809
      1861675.74      197271.671     1861568.423      197554.273
#Sta/Elev= 30
       0 1897.87    64.6  1858.8    99.4 1833.25   154.1 1796.05     184 1777.82
   213.8    1758   258.5 1729.75   283.4 1715.22   308.3 1698.29   333.2 1684.93
   338.2 1683.08   368.1 1681.35   394.6 1675.01     408 1673.49   409.6 1673.61
     423 1675.65   437.9 1674.89   447.9 1675.37   462.8 1678.31   477.8 1685.36
   522.5 1710.85   537.3 1716.48   552.2 1718.78   557.2 1721.14   581.9 1736.34
   636.4 1761.36   656.3 1767.96   755.4 1806.16   775.2 1812.12     795  1820.2
#Mann= 3 , 0 , 0
       0      .1       0   394.6    .045       0   409.6      .1       0
Bank Sta=394.6,409.6
XS Rating Curve= 0 ,0
Exp/Cntr=0.3,0.1

Type RM Length L Ch R = 1 ,3283.2  ,135.4,136.8,138.2
XS GIS Cut Line= 4
     1861852.614      196784.988     1861657.239      197010.478
     1861514.764      197200.126     1861322.417      197413.888
#Sta/Elev= 30
       0 1853.23    64.6 1836.41    94.5 1822.47   129.3 1800.93   159.1 1784.43
   193.9  1761.5   243.7 1726.12   278.5 1709.32   313.2 1685.51   323.1 1682.51
   382.4 1679.66   409.2 1668.41     412 1668.02   424.2 1668.76   441.7 1671.16
   456.5 1675.97   486.1 1690.92   505.9 1706.61   515.8 1712.46   520.7 1714.89
   535.6 1717.16   545.5 1720.63   560.4 1732.47   590.1 1747.85     600 1751.45
   619.8 1763.64   689.3 1792.78     714 1800.08   778.5 1814.38   823.1 1829.31
#Mann= 3 , 0 , 0
       0      .1       0   409.2    .045       0   424.2      .1       0
Bank Sta=409.2,424.2
XS Rating Curve= 0 ,0
Exp/Cntr=0.3,0.1

Type RM Length L Ch R = 1 ,3146.4  ,67.7,65.9,64.2
XS GIS Cut Line= 4
     1861707.935      196731.508     1861554.114      196931.833
     1861411.024      197099.964     1861285.821      197343.216
#Sta/Elev= 30
       0 1762.66    39.6 1761.32    74.3 1755.72     104 1744.24   128.8 1736.73
   148.6 1727.53   163.4 1723.21   188.2 1713.13   222.9 1695.53   252.6 1683.91
   262.4 1682.16   326.2 1678.71     336 1676.66   360.8 1667.24   375.2 1665.56
   375.8 1665.64     385 1667.77   394.8 1672.37   419.4 1689.32   448.8 1704.63
   473.4 1707.56   498.2 1720.36   503.2 1721.67     538  1723.3   552.9  1726.2
   562.9 1730.07   592.7 1748.36   677.3 1776.44   717.1 1791.66   746.9 1805.17
#Mann= 3 , 0 , 0
       0      .1       0   360.8    .045       0   375.8      .1       0
Bank Sta=360.8,375.8
XS Rating Curve= 0 ,0
Exp/Cntr=0.3,0.1

Type RM Length L Ch R = 1 ,3080.4  ,90.3,86,81.6
XS GIS Cut Line= 4
     1861623.844      196719.921     1861472.673      196918.078
      1861384.83      197038.606     1861247.959      197312.348
#Sta/Elev= 30
       0 1718.48      15 1717.99    34.9    1715    79.8 1710.44   124.6  1698.9
   159.5 1688.77   174.5 1685.73   204.4 1682.82   279.1 1678.63   313.7 1667.41
   323.8 1666.26   328.7  1666.6   338.7 1667.72   348.7 1670.21   358.6 1675.71
   373.5 1686.23   383.5 1689.43   393.4 1693.88   403.3    1696   432.9 1707.95
   447.7 1715.78   452.7 1717.68   472.4 1720.95   511.9 1725.08   521.8 1727.18
   556.3 1744.92     586 1756.16   600.8 1761.05   645.2 1779.23   704.4  1809.4
#Mann= 3 , 0 , 0
       0      .1       0   313.7    .045       0   328.7      .1       0
Bank Sta=313.7,328.7
XS Rating Curve= 0 ,0
Exp/Cntr=0.3,0.1

Type RM Length L Ch R = 1 ,2994.4  ,244,235.6,227.2
XS GIS Cut Line= 4
     1861500.455      196484.679     1861446.796      196749.394
      1861300.13      197064.191     1861184.503      197327.616
#Sta/Elev= 30
       0 1817.15   103.1 1772.62   186.6 1739.48   216.1 1725.21   245.5 1713.49
   260.3  1705.1   275.1 1698.57   309.8 1689.58   349.5 1686.67   359.4 1684.66
   369.3 1681.95   394.1 1669.06   449.9 1662.82   463.6 1660.57   464.9 1660.79
   513.2 1670.91   523.1 1675.02     538 1684.11   557.8 1689.79   572.7 1699.73
   582.7 1704.34   602.5 1708.85   622.4 1717.38   642.2 1720.06   657.1 1723.95
   686.8 1742.26   731.5 1760.86   850.5 1819.73   870.4  1827.6   905.1 1844.68
#Mann= 3 , 0 , 0
       0      .1       0   449.9    .045       0   464.9      .1       0
Bank Sta=449.9,464.9
XS Rating Curve= 0 ,0
Exp/Cntr=0.3,0.1