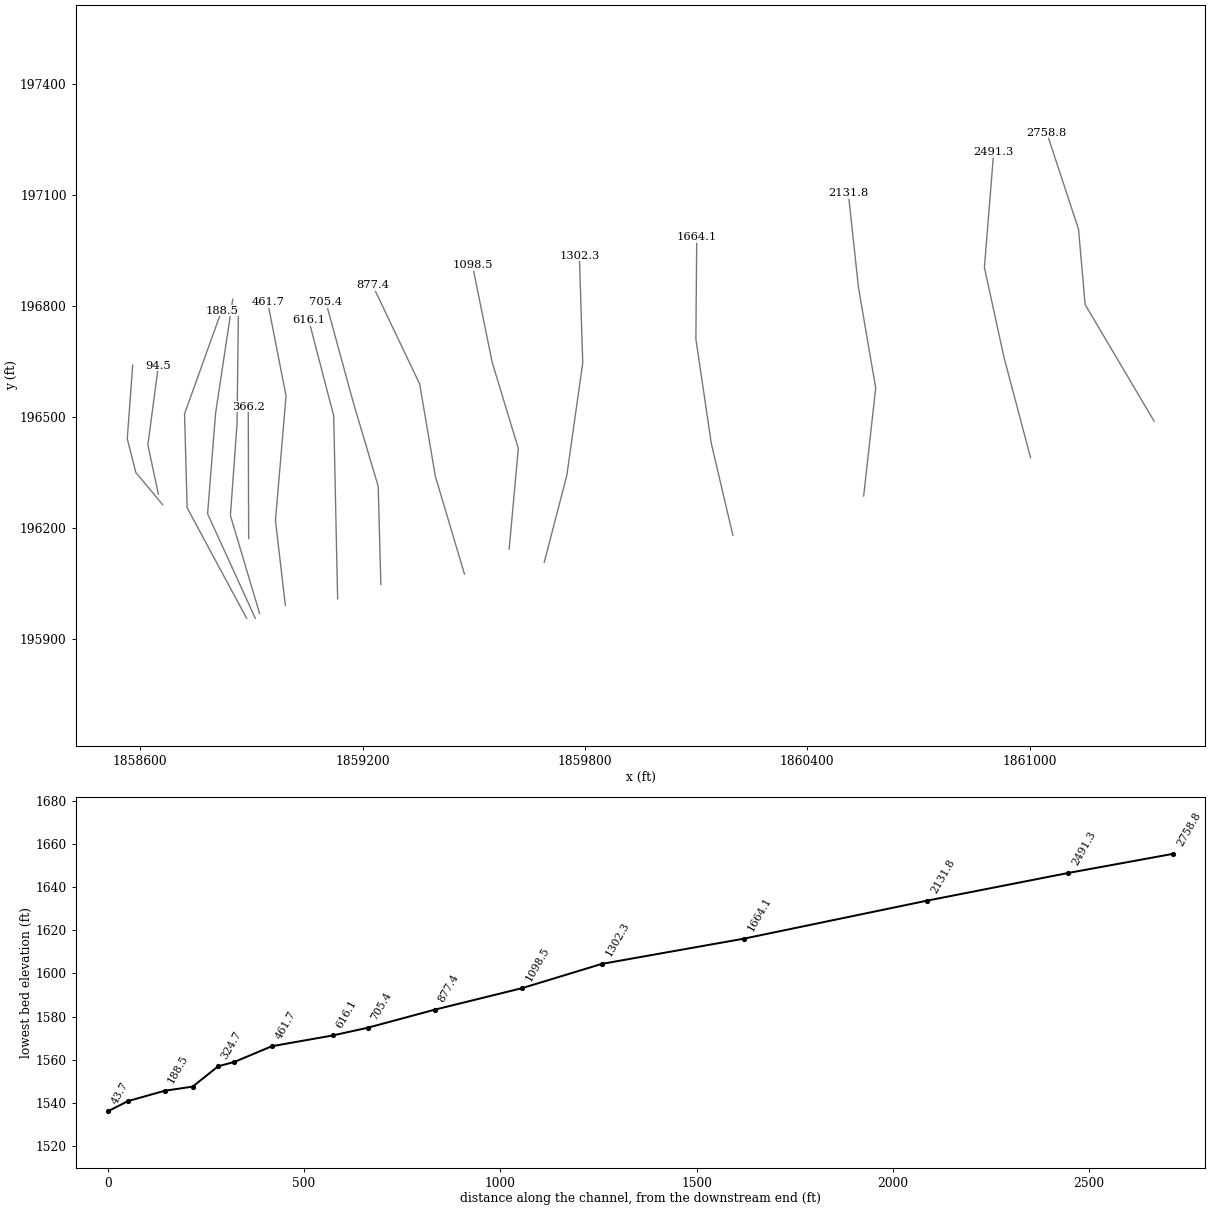
HEC-RAS study MillBr.prj: MillBr

--- MillBr.g01 (geometry) --- (continued)

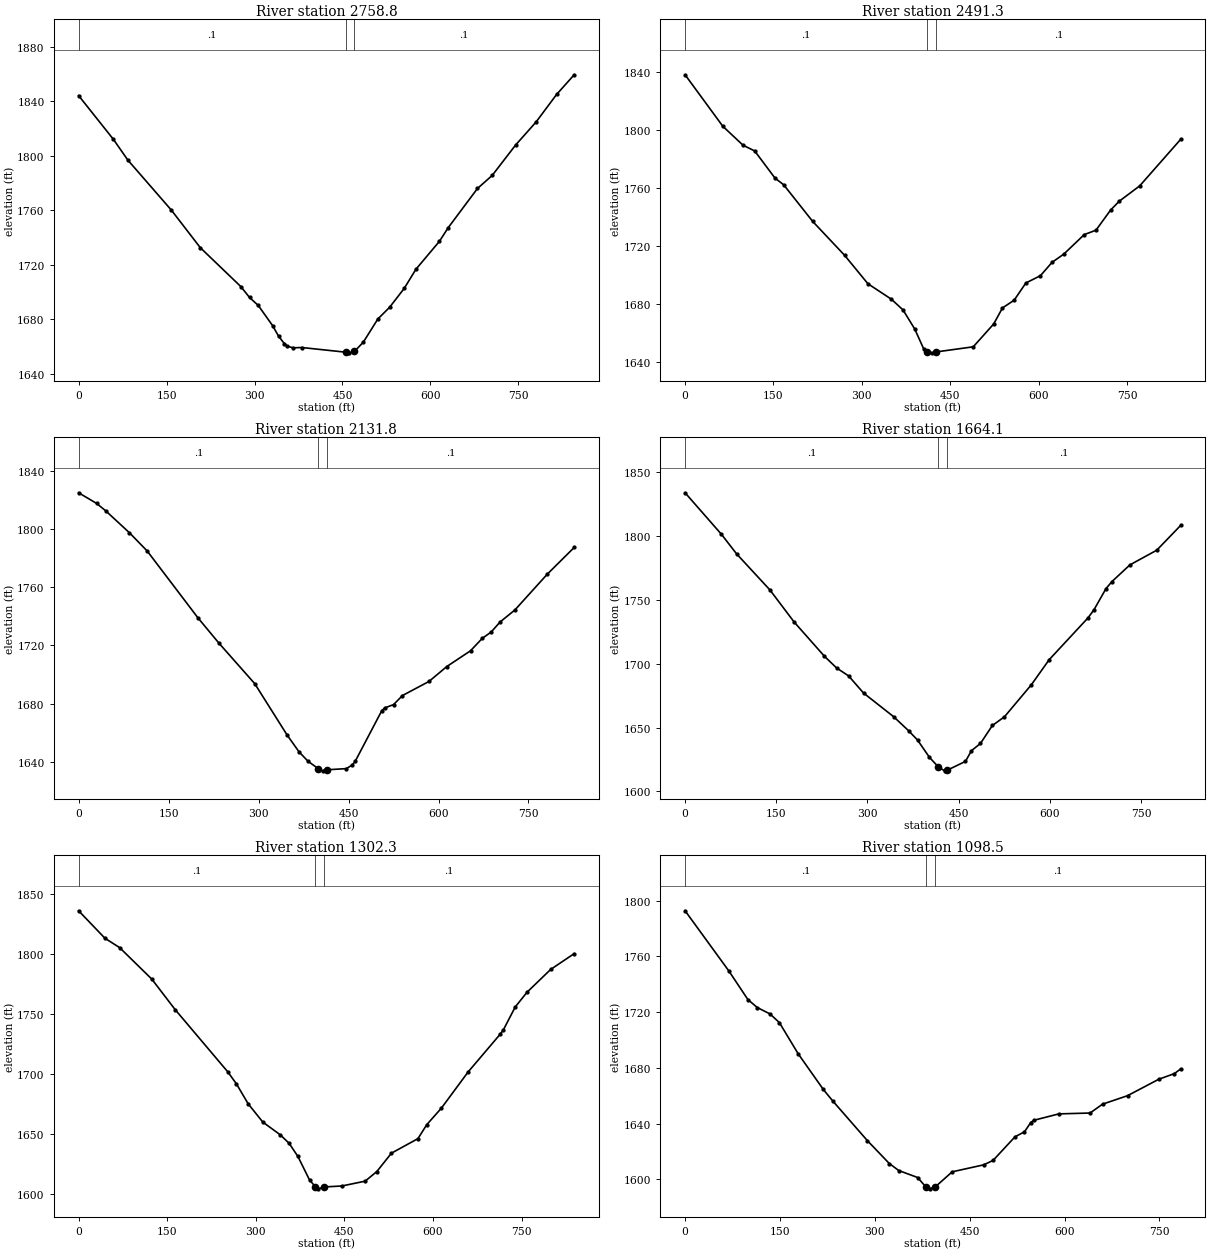
Type RM Length L Ch R = 1 ,2758.8  ,265.4,267.5,269.7
XS GIS Cut Line= 4
     1861335.902      196488.256     1861149.886      196803.053
        1861132.      197006.955     1861046.146      197268.094
#Sta/Elev= 30
       0 1844.15    59.3 1812.07      84 1796.83   158.1  1760.2   207.5 1732.62
   276.7 1704.06   291.5 1696.08   306.4 1690.23   331.1 1675.28   340.9 1667.76
   350.8 1662.28   355.8 1660.42   365.6 1659.15   380.6 1659.39   455.4 1655.96
   460.5 1655.48   470.4 1656.49   485.5 1663.27   510.4 1680.33   530.4 1688.88
   555.4  1702.8   575.3 1716.79   615.3 1737.24   630.3 1747.25   680.3 1776.04
   705.3 1785.56   745.3  1807.9   780.2 1824.79   815.2 1844.99   845.2 1859.43
#Mann= 3 , 0 , 0
       0      .1       0   455.4    .045       0   470.4      .1       0
Bank Sta=455.4,470.4
XS Rating Curve= 0 ,0
Exp/Cntr=0.3,0.1

Type RM Length L Ch R = 1 ,2491.3  ,360.5,359.5,358.8
XS GIS Cut Line= 4
     1861002.581       196389.56     1860930.839      196660.689
     1860878.016      196903.215     1860903.056      197214.435
#Sta/Elev= 30
       0 1838.27      64 1802.77    98.4 1789.68   118.1 1785.77   152.5 1767.08
   167.3 1762.43   216.5 1737.19   270.6 1713.86   310.2 1694.24     350 1683.58
   369.8 1676.18   389.7 1663.01   404.6 1649.59   411.3 1647.34   419.5  1646.6
   426.3 1647.24     489 1650.76   523.7 1666.53   538.6 1677.57   558.4 1682.88
   578.2 1694.73     603 1699.79   622.8 1709.02   642.7 1714.68   677.4 1728.13
   697.2 1731.12     722    1745   736.8 1751.14   771.5 1761.71   840.9 1793.75
#Mann= 3 , 0 , 0
       0      .1       0   411.3    .045       0   426.3      .1       0
Bank Sta=411.3,426.3
XS Rating Curve= 0 ,0
Exp/Cntr=0.3,0.1

Type RM Length L Ch R = 1 ,2131.8  ,468.4,467.6,466.5
XS GIS Cut Line= 4
     1860552.224      196285.885     1860584.682      196577.687
     1860538.178      196849.557     1860510.702      197104.831
#Sta/Elev= 30
       0 1824.71    29.9 1817.42    44.8 1812.45    84.6 1797.31   114.4 1784.69
     199 1738.79   233.9 1721.47   293.6 1693.65   347.8 1658.24   367.5 1646.81
   382.3 1640.42   399.6 1635.25   406.9 1633.78   414.6 1634.52   446.3  1635.3
   456.1 1637.79   461.1 1640.32   505.4 1675.05   510.3 1676.97   525.1 1679.28
   539.9 1685.48   584.2 1695.18   613.9 1705.42   653.4 1716.23   673.1 1724.79
   687.9 1729.12   702.7    1736   727.4 1744.25   781.7 1768.96   826.2 1787.15
#Mann= 3 , 0 , 0
       0      .1       0   399.6    .045       0   414.6      .1       0
Bank Sta=399.6,414.6
XS Rating Curve= 0 ,0
Exp/Cntr=0.3,0.1

Type RM Length L Ch R = 1 ,1664.1  ,368,361.8,355.6
XS GIS Cut Line= 4
     1860199.185      196179.958     1860141.105      196427.443
     1860099.447      196710.335     1860101.755      196985.492
#Sta/Elev= 30
       0 1833.74    59.8 1801.23    84.7 1785.95   139.6 1757.68   179.4 1732.59
   229.3 1705.77   249.2 1696.67     269 1690.42   293.6 1677.02     343 1658.54
   367.6 1647.58   382.4 1640.25   402.1 1626.65   416.5 1619.29   426.8 1616.13
   431.5 1616.68   461.3 1623.54   471.1 1631.87   485.9 1637.54   505.6 1651.65
   525.4 1658.41   569.6 1683.44   599.1 1703.16     663 1735.89   672.8 1742.25
   692.5 1758.75   702.3 1764.26   731.8 1777.29     776  1788.8   815.3 1808.18
#Mann= 3 , 0 , 0
       0      .1       0   416.5    .045       0   431.5      .1       0
Bank Sta=416.5,431.5
XS Rating Curve= 0 ,0
Exp/Cntr=0.3,0.1

Type RM Length L Ch R = 1 ,1302.3  ,193.9,203.8,213.7
XS GIS Cut Line= 4
     1859690.241      196106.824     1859751.186      196341.589
     1859794.113      196645.654     1859785.031      196935.085
#Sta/Elev= 30
       0 1836.25    44.6 1813.32    69.3 1805.59   123.8 1779.35   163.4  1753.9
   252.4 1702.09   267.3  1691.9   287.1 1675.34   311.9  1660.1   341.6 1649.44
   356.5 1642.39   371.3 1631.49   391.1 1611.78   401.1 1606.12     406 1604.45
   416.1 1606.05   445.6 1606.81   485.2 1610.85     505 1618.87   529.8  1634.2
   574.6  1646.3   589.6 1657.96   614.5 1671.83   659.5 1701.84   714.4 1733.64
   719.4 1737.07   739.4 1756.07   759.3 1768.31   799.3 1787.31   839.2 1800.52
#Mann= 3 , 0 , 0
       0      .1       0   401.1    .045       0   416.1      .1       0
Bank Sta=401.1,416.1
XS Rating Curve= 0 ,0
Exp/Cntr=0.3,0.1

Type RM Length L Ch R = 1 ,1098.5  ,224,221.1,218.3
XS GIS Cut Line= 4
     1859595.534      196142.307     1859620.267      196414.369
     1859549.602      196647.564     1859496.603      196909.026
#Sta/Elev= 30
       0 1792.81    69.5 1749.41    99.3 1729.07   114.2 1723.33   134.1  1718.8
     149 1712.59   178.8 1690.15   218.6  1664.5   233.4 1656.32   288.1 1627.86
   322.9 1611.36   337.8 1606.34   367.7 1601.31   380.7 1594.57   387.6 1593.18
   395.7 1594.64   422.4 1605.41   472.1  1610.4     487 1613.58   521.8  1630.6
   536.6 1634.09   546.5 1640.74   551.4 1642.39     591 1646.99   640.4 1647.61
   660.1 1653.97   699.6 1660.05     749 1671.85   773.8 1675.93   783.6 1679.25
#Mann= 3 , 0 , 0
       0      .1       0   380.7    .045       0   395.7      .1       0
Bank Sta=380.7,395.7
XS Rating Curve= 0 ,0
Exp/Cntr=0.3,0.1

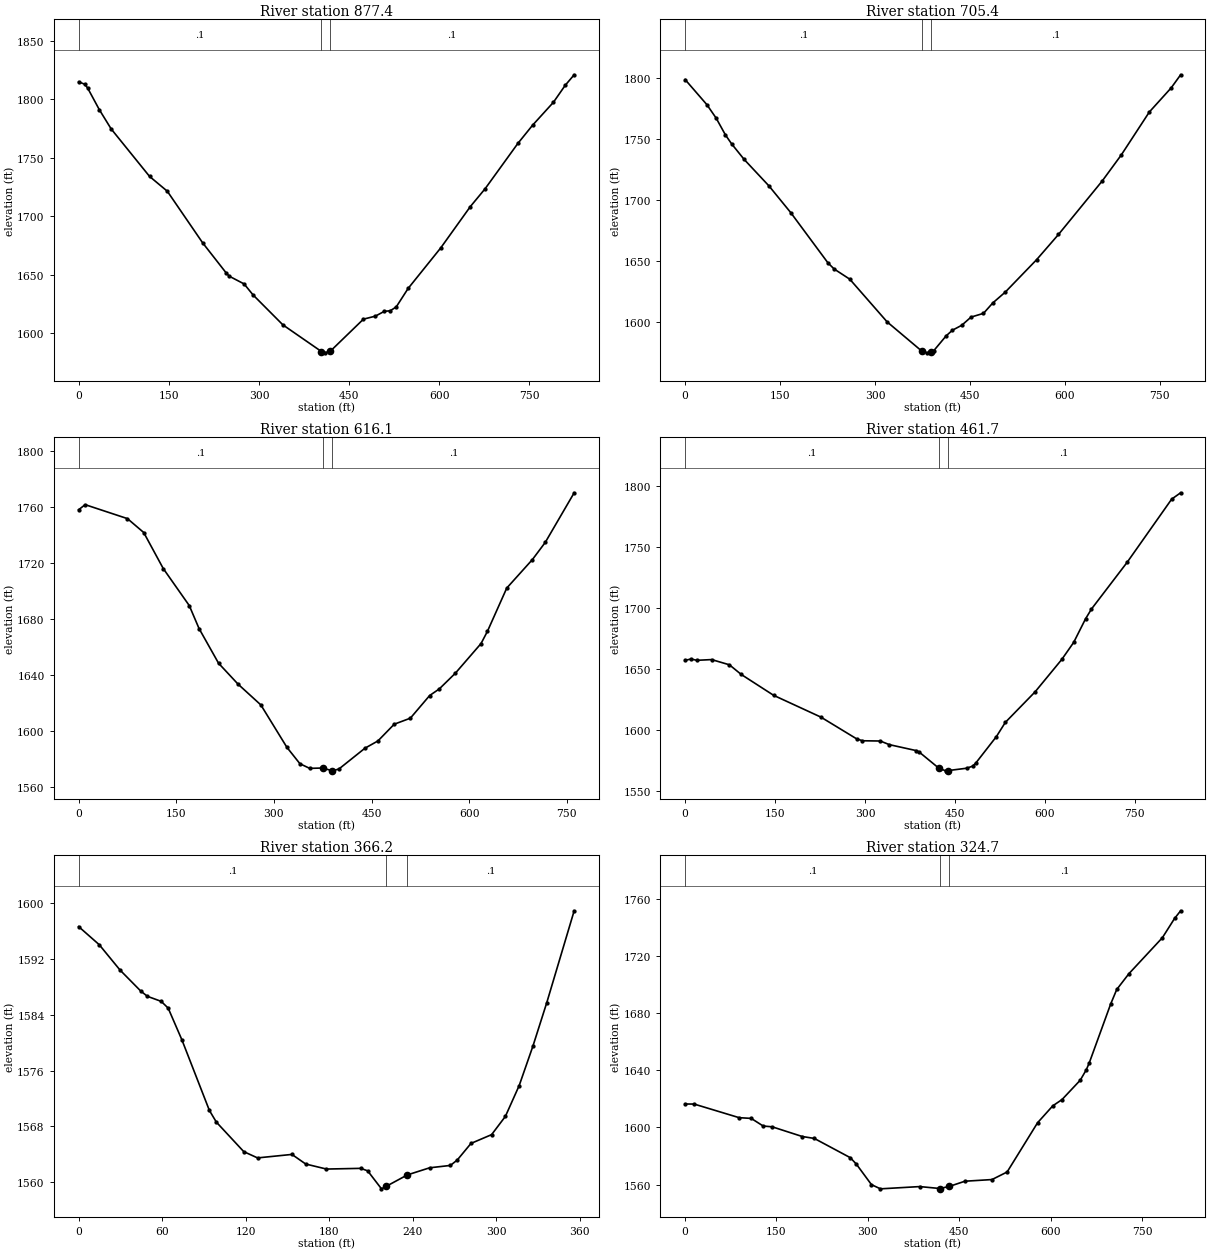
Type RM Length L Ch R = 1 ,877.4   ,169.3,172,174.7
XS GIS Cut Line= 4
     1859474.939      196075.065     1859396.424      196338.894
     1859354.113      196588.419     1859226.852      196855.733
#Sta/Elev= 30
       0 1814.85     9.8 1812.88    14.8 1809.74    34.4 1791.07    54.1 1774.63
     118 1734.02   147.5 1721.39   206.4 1677.21   245.8 1651.34   250.7 1648.73
   275.3 1642.15   290.2 1632.75   339.8 1607.18   403.9 1584.41   409.2 1583.27
   418.9 1584.75   473.8 1612.05   493.6 1614.61   508.5 1618.73   518.4 1619.22
   528.4 1622.52   548.1 1638.26   602.4 1672.94   651.7 1708.28   676.4  1723.6
   730.7  1762.2   755.3 1777.84   789.9 1797.38   809.6 1811.94   824.4 1820.88
#Mann= 3 , 0 , 0
       0      .1       0   403.9    .045       0   418.9      .1       0
Bank Sta=403.9,418.9
XS Rating Curve= 0 ,0
Exp/Cntr=0.3,0.1

Type RM Length L Ch R = 1 ,705.4   ,99.5,89.3,83.5
XS GIS Cut Line= 4
     1859249.274      196046.909     1859242.208      196311.904
     1859175.075      196538.033     1859100.877      196810.095
#Sta/Elev= 30
       0 1798.81    34.4 1778.23    49.1 1767.16    63.8 1753.36    73.6 1746.04
    93.3 1733.35   132.5 1711.64   166.9 1689.77   225.8 1648.51   235.6 1643.51
   260.2  1635.2   319.2 1600.22   373.6 1576.44     383 1574.84   388.6 1575.38
   392.9 1576.59   412.5 1588.77   422.4 1593.38   437.1 1597.42   451.8 1604.13
   471.5  1607.2   486.2 1615.74   505.9 1624.61   555.4 1651.16     590 1671.85
   659.3 1715.82     689 1736.85   733.5 1772.18   768.1 1792.01     783 1802.71
#Mann= 3 , 0 , 0
       0      .1       0   373.6    .045       0   388.6      .1       0
Bank Sta=373.6,388.6
XS Rating Curve= 0 ,0
Exp/Cntr=0.3,0.1

Type RM Length L Ch R = 1 ,616.1   ,157.3,154.5,151.7
XS GIS Cut Line= 3
     1859132.676      196008.043     1859122.076        196502.7
     1859054.944      196760.629
#Sta/Elev= 30
       0 1757.94      10 1761.61      75 1751.62     100 1741.69     130 1715.94
     170 1689.43     185 1673.04     215 1648.21     245 1633.23     280 1618.38
     320 1588.08     340 1576.36     355 1573.03     375 1573.28   389.9 1571.26
     390 1571.26   399.9 1572.56   439.9 1587.43   459.9 1592.65   484.9  1604.6
   509.7 1608.91   539.3 1625.09   554.1 1629.82   578.8 1641.05   618.3 1662.29
   628.2  1671.1   657.8 1701.95   697.3 1722.38     717 1734.64   761.4  1770.1
#Mann= 3 , 0 , 0
       0      .1       0     375    .045       0     390      .1       0
Bank Sta=375,390
XS Rating Curve= 0 ,0
Exp/Cntr=0.3,0.1

Type RM Length L Ch R = 1 ,461.7   ,94.4,95.5,96
XS GIS Cut Line= 4
     1858991.596      195990.085     1858964.888      196219.963
     1858993.506      196556.223     1858944.001      196809.095
#Sta/Elev= 30
       0 1657.06     9.8  1658.1    19.7 1657.06    44.3 1657.65    73.9 1653.37
    93.6 1645.46   147.7  1628.3   226.5 1610.42     286 1592.61   295.9 1590.99
   325.7 1590.79   340.6 1587.82   385.3 1582.94   390.2 1581.85   423.5 1568.39
   434.9  1566.3   438.5  1566.5   469.6 1568.44   479.6 1570.15   484.5 1572.44
   519.3 1594.45   534.2  1606.1   583.8 1631.14   628.4 1657.81   648.2 1671.77
     668 1691.14   677.9 1699.19   737.4 1737.55   811.7 1789.44   826.6 1794.62
#Mann= 3 , 0 , 0
       0      .1       0   423.5    .045       0   438.5      .1       0
Bank Sta=423.5,438.5
XS Rating Curve= 0 ,0
Exp/Cntr=0.3,0.1

Type RM Length L Ch R = 1 ,366.2   ,43.2,41.5,40.6
XS GIS Cut Line= 2
     1858892.563      196170.997     1858891.513      196526.927
#Sta/Elev= 30
       0 1596.66    14.8 1594.06    29.7 1590.43    44.5 1587.43    49.4 1586.65
    59.3 1585.93    64.3 1584.96    74.2 1580.39    93.9 1570.28    98.9  1568.6
   118.6 1564.36   128.5 1563.46   153.2 1563.96   163.1 1562.58     178 1561.86
   202.7 1561.96   207.6  1561.6   217.5 1559.02   221.1  1559.4   236.1 1561.02
   252.1 1562.04     267 1562.38   271.9 1563.15   281.8 1565.54   296.6  1566.8
   306.5 1569.42   316.4 1573.84   326.3 1579.52   336.2 1585.73   355.9 1598.93
#Mann= 3 , 0 , 0
       0      .1       0   221.1    .045       0   236.1      .1       0
Bank Sta=221.1,236.1
XS Rating Curve= 0 ,0
Exp/Cntr=0.3,0.1

Type RM Length L Ch R = 1 ,324.7   ,64.2,65,65.4
XS GIS Cut Line= 4
     1858922.011      195968.757     1858843.312      196233.473
     1858861.198      196480.302     1858864.775      196770.059
#Sta/Elev= 30
       0 1616.32    14.8 1616.28    88.8 1606.75   108.5 1606.26   128.2 1600.92
     143 1600.36   192.3 1593.59   212.1 1592.24   271.2 1578.77   281.1 1574.28
   305.9 1559.93   320.7 1556.99   385.1 1558.57   418.3 1557.22   433.3 1558.63
   459.3 1562.32   503.8 1563.48   528.6 1568.78   578.6 1603.23   603.6 1615.07
   618.6 1619.38   648.6 1632.96   658.5 1640.22   663.5 1645.17   698.5 1686.18
   708.5  1696.4   728.5 1707.45   783.4  1732.6   803.4 1746.06   813.4 1751.45
#Mann= 3 , 0 , 0
       0      .1       0   418.3    .045       0   433.3      .1       0
Bank Sta=418.3,433.3
XS Rating Curve= 0 ,0
Exp/Cntr=0.3,0.1

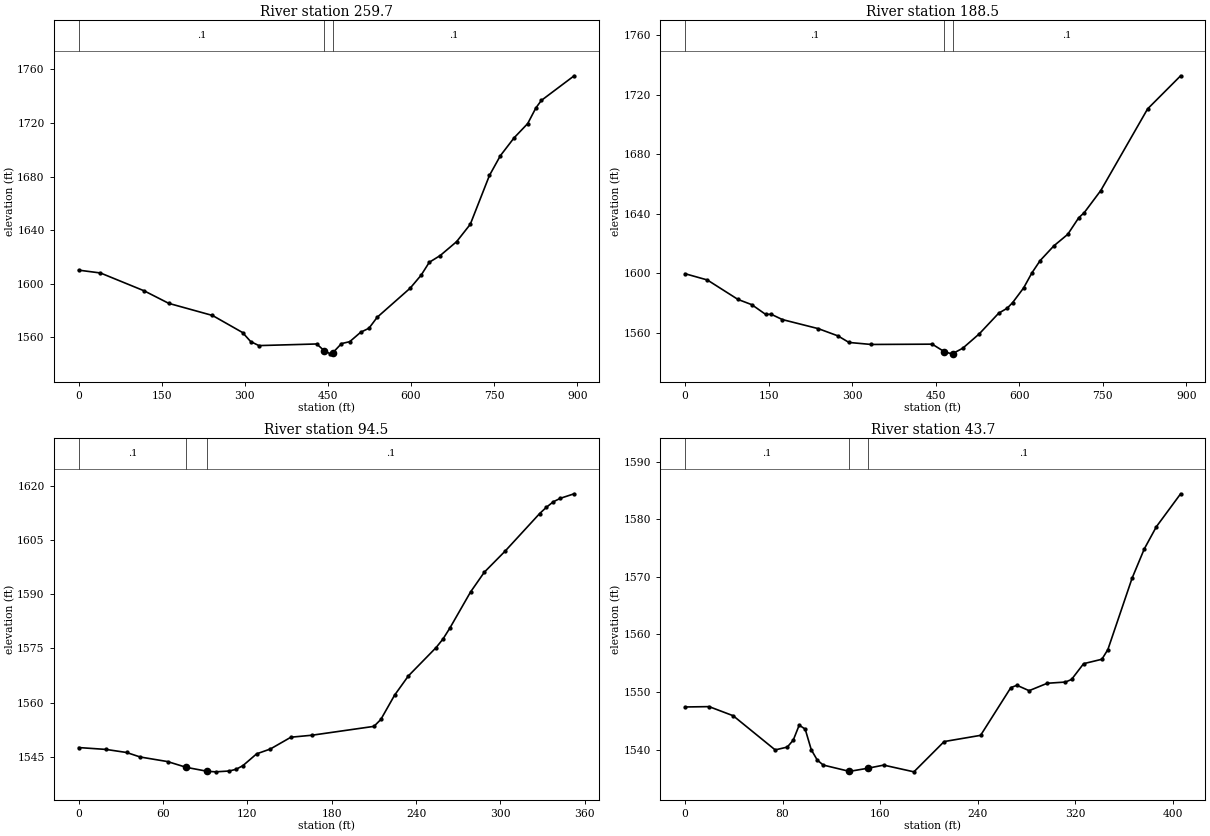
Type RM Length L Ch R = 1 ,259.7   ,69,71.3,73.6
XS GIS Cut Line= 4
     1858910.535      195955.248     1858781.754      196237.849
     1858803.386      196510.006     1858849.722      196817.362
#Sta/Elev= 30
       0 1610.08    39.4 1607.96   118.3 1594.62   162.7 1585.27   241.6 1576.23
   295.8  1563.5   310.6  1556.7   325.4 1553.73   429.7 1554.94   443.6 1549.79
   454.5 1547.57   458.6  1548.3   474.4 1555.22   489.3 1556.65   509.1  1563.7
     524 1566.69   538.9 1574.89   598.4 1596.62   618.1 1606.28   632.9 1615.95
   652.6 1620.98   682.2 1631.35   706.9 1644.33   741.5 1680.83   761.2 1695.55
   785.9 1708.87   810.5 1719.53   825.3 1731.24   835.2 1736.84   894.4 1755.24
#Mann= 3 , 0 , 0
       0      .1       0   443.6    .045       0   458.6      .1       0
Bank Sta=443.6,458.6
XS Rating Curve= 0 ,0
Exp/Cntr=0.3,0.1

Type RM Length L Ch R = 1 ,188.5   ,89.7,94,98.3
XS GIS Cut Line= 4
     1858887.124      195955.273      1858726.58      196253.985
     1858719.597      196507.679     1858819.678      196786.975
#Sta/Elev= 30
       0 1599.55    39.9 1595.35    94.8 1582.28   119.7 1578.73   144.6 1572.19
   154.6 1572.28   174.6 1568.71   239.4 1562.57   274.3 1557.74   294.2 1553.31
   334.1 1551.96   443.6 1552.16   465.5 1547.07   478.5 1545.65   480.5 1545.85
   498.4 1549.41   528.2 1559.13     563 1573.01     578 1576.28   587.9 1580.07
   607.8 1590.04   622.6 1600.12   637.4  1608.4   662.1 1618.33   686.9 1626.04
   706.6 1637.17   716.5 1640.62   746.2  1655.5   830.3 1710.45   889.6 1732.72
#Mann= 3 , 0 , 0
       0      .1       0   465.5    .045       0   480.5      .1       0
Bank Sta=465.5,480.5
XS Rating Curve= 0 ,0
Exp/Cntr=0.3,0.1

Type RM Length L Ch R = 1 ,94.5    ,49.8,50.7,51.7
XS GIS Cut Line= 3
     1858648.977      196290.691     1858620.629      196424.033
     1858648.977      196638.221
#Sta/Elev= 30
       0 1547.55    19.5 1547.03    34.1 1546.18    43.8 1544.93    63.3 1543.66
    76.5 1542.07    91.5 1540.97    97.4 1540.82   107.1 1541.05     112 1541.53
   116.8 1542.53   126.6 1545.81   136.3 1547.14     151 1550.42   165.8 1550.96
     210 1553.42   214.9 1555.33   224.7 1562.07   234.5  1567.4   254.2 1575.25
   259.1 1577.62     264 1580.66   278.7 1590.65   288.5 1596.14   303.3 1601.98
   327.8 1612.37   332.7 1614.15   337.6 1615.66   342.6 1616.62   352.4 1617.87
#Mann= 3 , 0 , 0
       0      .1       0    76.5    .045       0    91.5      .1       0
Bank Sta=76.5,91.5
XS Rating Curve= 0 ,0
Exp/Cntr=0.3,0.1

Type RM Length L Ch R = 1 ,43.7    ,47.8,43.7,39.7
XS GIS Cut Line= 4
     1858660.526      196262.342     1858588.081      196349.487
     1858564.982      196440.832     1858579.681      196639.271
#Sta/Elev= 30
       0  1547.4    19.7 1547.46    39.4 1545.88    73.9 1539.94    83.8 1540.43
    88.7 1541.63    93.6 1544.24    98.5 1543.56   103.5 1539.97   108.4 1538.18
   113.3 1537.31   134.8 1536.21   149.8 1536.75   162.9  1537.3   187.7 1536.13
   212.5 1541.39   242.4 1542.47   267.2 1550.76   272.2 1551.17   282.2 1550.23
   297.1 1551.52     312 1551.73     317 1552.18   326.9 1554.92   341.9 1555.69
   346.8 1557.37   366.7 1569.79   376.7 1574.87   386.6 1578.72   406.5 1584.44
#Mann= 3 , 0 , 0
       0      .1       0   134.8    .045       0   149.8      .1       0
Bank Sta=134.8,149.8
XS Rating Curve= 0 ,0
Exp/Cntr=0.3,0.1

Chan Stop Cuts=-1
Use User Specified Reach Order=0